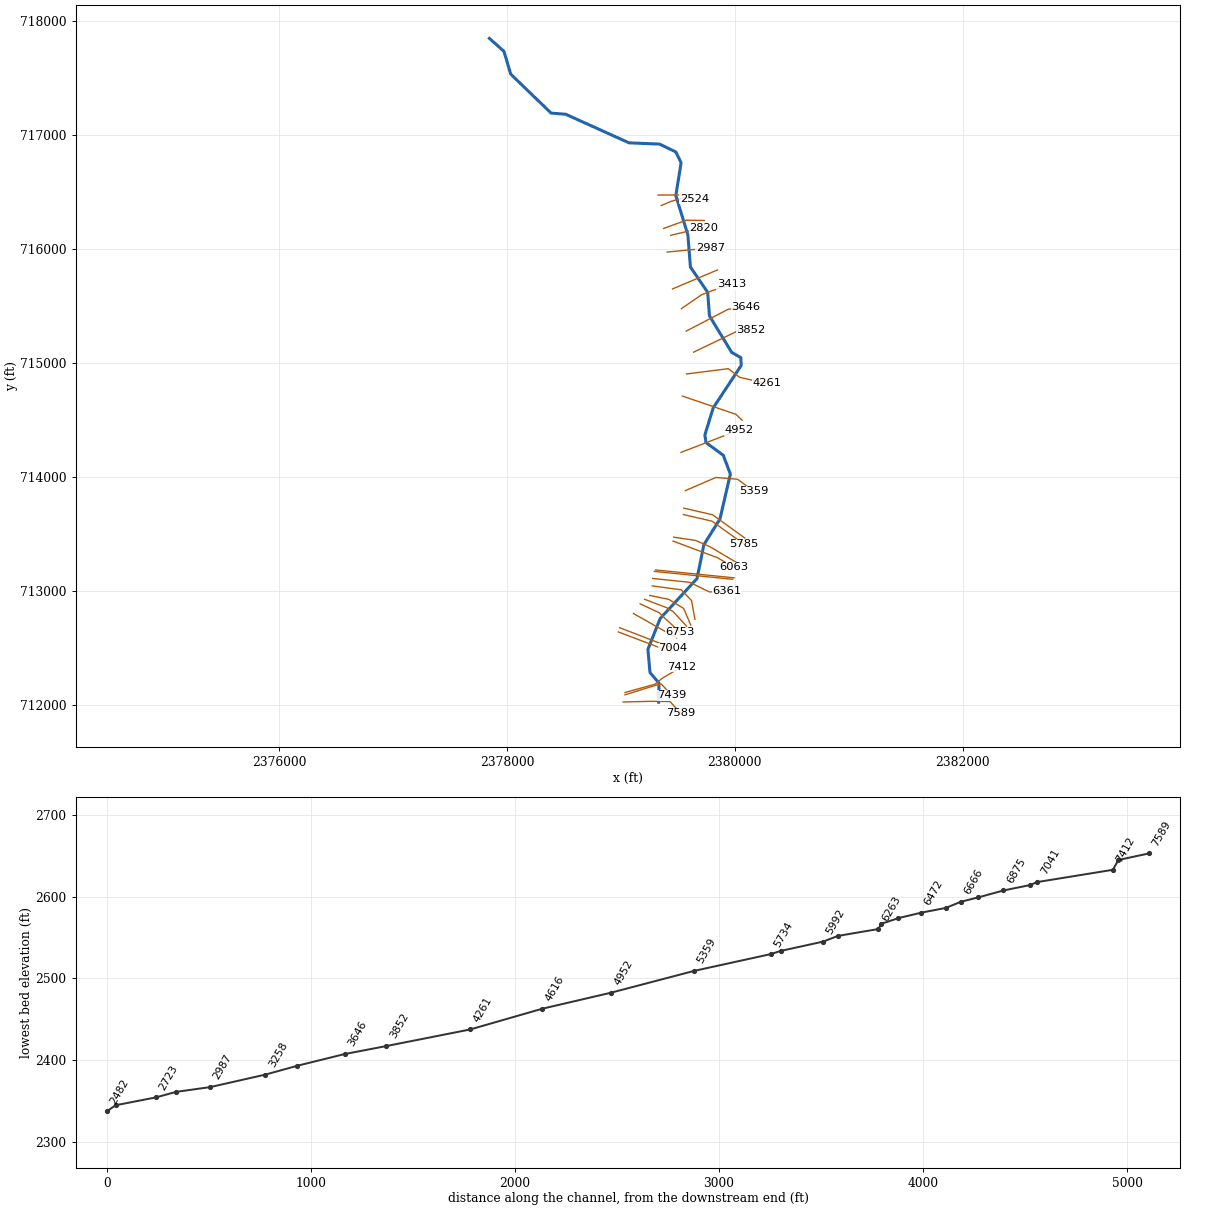
--- SNYDERRN.prj (project) ---

Proj Title=SNYDERRN
Current Plan=p01
Default Exp/Contr=0,0
English Units
Geom File=g01
Flow File=f01
Plan File=p01
BEGIN DESCRIPTION:
----------MODEL BY WOOD PLC 2022----------
AFH study
Randolph County, WV
HEC-RAS Version: RAS 6.2
Vertical Datum: NAVD88
Projection: NAD 1983 StatePlane West Virginia S FIPS 4702 (US Feet)
Terrain: 1-meter LIDAR (FEMA Region III 3DEP collected 2016-2018)
Land Use: 2019 NLCD
Hydrologic Method:
WV SIR2010-5033 regression equations
Additional Model Notes:
Main stem is LAURELFK; had to place DS XS in main stem channel to achieve tie-in
END DESCRIPTION:
DSS Export Rating Curves= 0
DSS Export Rating Curve Sorted= 0
DSS Export Volume Flow Curves= 0
DXF OffsetX= 0
DXF OffsetY= 0
DXF ScaleX= 0
DXF ScaleY= 0

--- SNYDERRN.p01 (plan) ---

Plan Title=Floodplain
Program Version=6.20
Short Identifier=Floodplain
Geom File=g01
Flow File=f01
Subcritical Flow
K Sum by GR= 0
Std Step Tol= 0.01
Critical Tol= 0.01
Num of Std Step Trials= 20
Max Error Tol= 0.3
Flow Tol Ratio= 0.001
Split Flow NTrial= 30
Split Flow Tol= 0.02
Split Flow Ratio= 0.02
Log Output Level= 0
Friction Slope Method= 1
Unsteady Friction Slope Method= 2
Unsteady Bridges Friction Slope Method= 1
Parabolic Critical Depth
Global Vel Dist= 0 , 0 , 0
Global Log Level= 0
CheckData=True
Encroach Param=-1 ,0,0, 0
Mapping Interval=1HOUR
Computation Time Step Use Courant=        0
Computation Time Step Use Time Series=    0
Computation Time Step Count To Double=0
Computation Time Step Max Doubling=0
Computation Time Step Max Halving=0
Computation Time Step Residence Courant=0
Run HTab= 0
Run UNet= 0
Run Sediment= 0
Run PostProcess= 0
Run WQNet= 0
Run RASMapper=-1
UNET Theta= 0
UNET Theta Warmup= 0
UNET ZTol= 0
UNET ZSATol= 0
UNET MxIter= 0
UNET Max Iter WO Improvement= 0
UNET MaxInSteps= 0
UNET DtIC= 0
UNET DtMin= 0
UNET MaxCRTS= 0
UNET WFStab= 0
UNET SFStab= 0
UNET WFX= 1
UNET SFX= 1
UNET Gravity=32.174
UNET 1D Methodology=Finite Difference
UNET DSS MLevel= 1
UNET Pardiso=0
UNET DZMax Abort= 0
UNET Use Existing IB Tables= 0
UNET Froude Reduction=False
UNET Froude Limit= 0
UNET Froude Power= 0
UNET D1 Cores= 0
UNET WindReference=Eulerian
UNET WindDragFormulation=Hsu (1988)
UNET D2 Coriolis=0
UNET D2 Cores= 0
UNET D2 Theta= 1
UNET D2 Theta Warmup= 1
UNET D2 Z Tol= 0.01
UNET D2 Volume Tol= 0.01
UNET D2 Max Iterations= 20
UNET D2 Equation= 0
UNET D2 RampUpFraction=0.1
UNET D2 TimeSlices= 1
UNET D2 Turbulence Formulation=Non-Conservative (original)
UNET D2 Eddy Viscosity=0.3
UNET D2 Transverse Eddy Viscosity=0.1
UNET D2 Smagorinsky Mixing=0
UNET D2 BCVolumeCheck=0
UNET D2 Cores=0
UNET D2 SolverType=PARDISO (Direct)
UNET D2 Minimum Iterations= 2147483647
UNET D2 Maximum Iterations= 2147483647
UNET D2 Restart Number= 10
UNET D2 Relaxation Coeff=1.3
UNET D2 SOR Precondition Iterations= 10
UNET D2 ILUT Maximum Fill= 8
UNET D2 ILUT Tolerance=1E-08
UNET D1D2 MaxIter= 0
UNET D1D2 ZTol=0.01
UNET D1D2 QTol=0.1
UNET D1D2 MinQTol=1
Write IC File= 0
Write IC File at Fixed DateTime=0
Write IC File at Sim End=0
Echo Input=False
Echo Parameters=False
Echo Output=False
Write Detailed= 0
HDF Write Warmup=0
HDF Write Time Slices=0
HDF Flush=0
HDF Compression= 1
HDF Chunk Size= 1
HDF Spatial Parts= 1
HDF Use Max Rows=0
HDF Fixed Rows= 1
Calibration Method= 0
Calibration Iterations= 20
Calibration Max Change=0.05
Calibration Tolerance=0.2
Calibration Maximum=1.5
Calibration Minimum=0.5
Calibration Optimization Method= 1
WQ AD Non Conservative
WQ ULTIMATE=-1
WQ Max Comp Step=1HOUR
WQ Output Interval=15MIN
WQ Output Selected Increments= 0
WQ Output face flow=0
WQ Output face velocity=0
WQ Output face area=0
WQ Output face dispersion=0
WQ Output cell volume=0
WQ Output cell surface area=0
WQ Output cell continuity=0
WQ Output cumulative cell continuity=0
WQ Output face conc=0
WQ Output face dconc_dx=0
WQ Output face courant=0
WQ Output face peclet=0
WQ Output face adv mass=0
WQ Output face disp mass=0
WQ Output cell mass=0
WQ Output cell source sink temp=0
WQ Output nsm pathways=0
WQ Output nsm derived pathways=0
WQ Create Restart=0
WQ Fixed Restart=0
WQ System Summary=0
WQ Write To DSS=0
Sorting and Armoring Iterations= 10
XS Update Threshold= 0.02
Bed Roughness Predictor= 0
Hydraulics Update Threshold= 0.02
Energy Slope Method= 1
Volume Change Method= 1
Sediment Retention Method= 0
Sediment TS Multiplier= 1
Warm Up Method= 0
XS Weighting Method= 0
Number of US Weighted Cross Sections= 1
Number of DS Weighted Cross Sections= 1
Upstream XS Weight=0
Main XS Weight=1
Downstream XS Weight=0
Number of DS XS's Weighted with US Boundary= 1
Upstream Boundary Weight= 1
Weight of XSs Associated with US Boundary= 0
Number of US XS's Weighted with DS Boundary= 1
Downstream Boundary Weight= 0.5
Weight of XSs Associated with DS Boundary= 0.5
Percentile Method= 0
Sediment Output Level= 3
Mass or Volume Output= 0
Output Increment Type= 1
Profile and TS Output Increment= 1
Transport Output Increment 1
XS Output Flag= 0
XS Output Increment= 10
Read HDF5 Sediment Hotstart= 0
Sediment Hotstart Type= 0
Write Gradation File= 0
Read Gradation Hotstart= 0
Write HDF5 File= 1
Write Binary Output= 1
Write DSS Sediment File= 0
DSS Sediment Output Type= 1
SV Curve= 0
Specific Gage Flag= 0
Subcell Erosion Methods= 0
Subcell Deposition Methods= 0
Advection Scheme= 1
Matrix Solver= 0
Implicit Weighting Factor= 1
Maximum Outer Loop Convergence Iterations= 5
Convergence Maximum Absolute= 0.001
Convergence RMSE= 0.0001
Grain Fractions Max Abs Error= 0.001
Max Subgrid Regions= 1
Max Subgrid Length Scale= 3.402823E+38
Initial Layer Thickness= 3.402823E+38
Min Layer Thickness= 3.402823E+38
Max Layer Thickness= 3.402823E+38
Number of Layers= 5

--- SNYDERRN.f01 (steady flow) ---

Flow Title=Flow
Program Version=6.20
Number of Profiles= 1
Profile Names=P100yr
River Rch & RM=SNYDERRN,Main,7589
     362
River Rch & RM=SNYDERRN,Main,5359
     475
River Rch & RM=SNYDERRN,Main,2180
     595
Boundary for River Rch & Prof#=SNYDERRN,Main            , 1
Up Type= 0
Dn Type= 3
Dn Slope=0.04313
DSS Import GetInterval= 0
DSS Import GetPeak= 0
DSS Import FillOption= 0

--- SNYDERRN.g01 (geometry) ---

Geom Title=Geometry
Program Version=6.20

River Reach=SNYDERRN        ,Main
Reach XY= 30
2379331.07799999712025.5840000212379334.55499999712193.090000004
2379255.41500001712285.6690000152379237.32700001712488.778000012
2379344.47399999712759.3770000192379668.00880822713110.180786019
2379728.78990563 713408.404912292379869.70473472713633.488370265
     2379960.939714028.3620000182379898.43900003714192.251000002
2379746.53762977 714304.108000012379737.32800001714370.723000005
2379810.13677452 714607.694174932380056.07699999714981.140000001
2380052.60500005715049.1949999932379972.74400002715095.029000014
2379777.51899999715415.2539999932379761.89400002715621.851000011
2379610.41800003715844.5080000012379587.75109935716127.316037773
      2379482.38716470.8100000022379528.49100003716759.269999996
2379482.48400003716854.2350000142379340.05500004716923.028999999
2379071.39200002716934.214000016 2378515.6082439717185.071602935
2378388.00089537717194.9264278712378033.51299998717536.996000007
2377973.93300003717737.2419999992377846.01935157717851.238244036

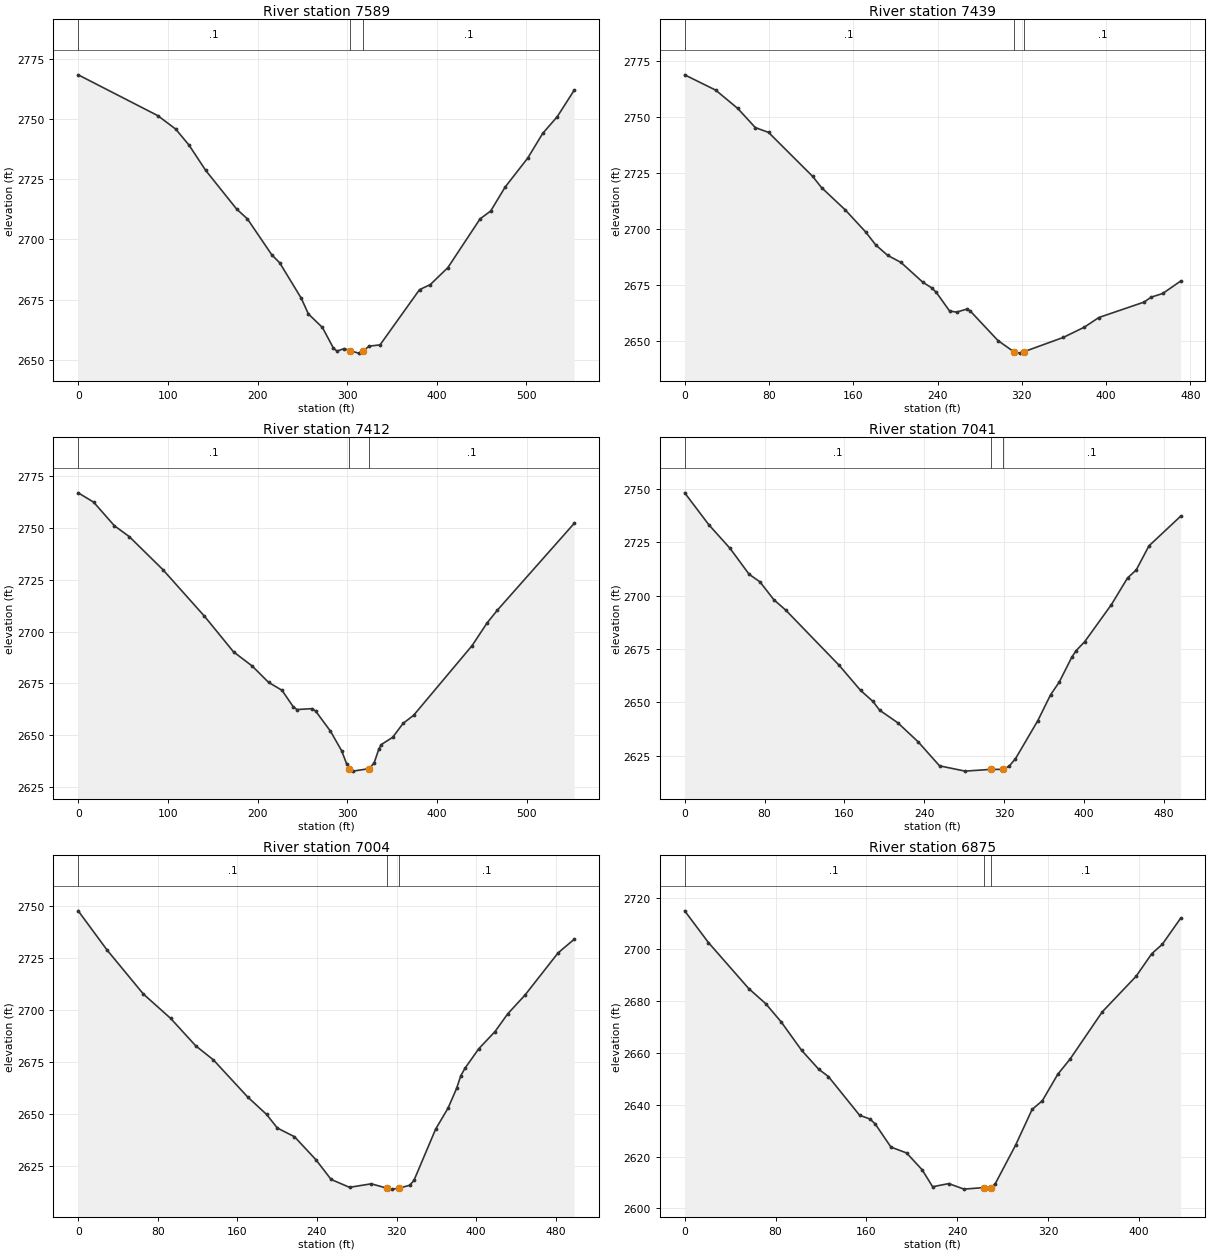
Type RM Length L Ch R = 1 ,7589    ,150.4,150.4,152.5
XS GIS Cut Line= 4
2379019.53739234712027.2919161862379263.76619376712033.212614402
2379431.76600565712030.9923525712379527.23726439711927.380133786
#Sta/Elev= 30
       0 2768.42    88.7 2751.47   108.7 2745.88   123.6  2739.2   142.2 2728.69
   176.7 2712.61   188.7 2708.54     216 2693.55   224.7 2690.29   248.7  2675.6
   256.8 2668.98   272.4 2663.38   284.7 2654.78   288.7 2653.56   296.7 2654.59
  303.252653.736   312.7 2652.71   317.7 2653.72   324.7 2655.61   336.7 2656.15
   380.7  2679.1   392.7  2681.2   412.3 2688.25   448.3 2708.55   460.1  2711.8
   476.2 2721.75   501.5 2733.85   518.1 2744.06   534.4 2751.04   553.2 2762.01
#Mann= 3, -1 ,  0
       0     0.1       0  303.25   0.045       0   317.7     0.1       0
Bank Sta=303.25,317.7
XS Rating Curve= 0 ,0
Exp/Cntr(USF)=0,0
Exp/Cntr=0.3,0.1

Type RM Length L Ch R = 1 ,7439    ,24.4,27,33.3
XS GIS Cut Line= 4
2379036.15201036712090.1755393462379308.07191734712174.880748467
2379353.03183691 712186.15466375 2379449.0301983712084.945497166
#Sta/Elev= 30
       0 2768.79    29.4 2761.97    50.4 2753.79    67.1 2745.25    79.6 2743.12
   121.5 2723.49   129.9 2718.51   152.6 2708.47   171.8 2698.71   181.3 2692.95
   192.7 2688.28   205.3 2685.14     226 2676.32   234.6 2673.75   238.9 2671.74
   251.4  2663.5     258 2662.98   267.6  2664.3   270.8 2663.61   297.3 2650.33
  312.38 2645.31   317.9  2644.7     322 2645.32   359.5 2651.73   379.3 2656.27
   393.1 2660.58   435.9 2667.44   442.8 2669.66   453.8 2671.31   470.7 2676.83
#Mann= 3, -1 ,  0
       0     0.1       0  312.38   0.045       0     322     0.1       0
Bank Sta=312.38,322
XS Rating Curve= 0 ,0
Exp/Cntr(USF)=0,0
Exp/Cntr=0.3,0.1

Type RM Length L Ch R = 1 ,7412    ,376.1,370.6,358.8
XS GIS Cut Line= 4
2379037.29948699712110.9217784912379299.37685737712183.434342331
2379360.71762705 712233.776266482379533.89804988712336.648397988
#Sta/Elev= 30
       0 2766.97    17.2 2762.47    40.3 2751.09    56.9 2745.85    94.3 2729.94
   140.7 2707.43   173.1 2690.24   193.9  2683.4   212.2  2675.5   227.1  2671.7
   239.5 2663.85   243.7  2662.4   260.3 2662.83   264.5 2661.72     281 2652.05
   293.6 2642.51   299.3    2636   302.12633.947   306.2 2632.69   324.62633.915
   329.9 2636.78   335.1 2643.41   337.7 2645.49   350.5 2649.03   362.1 2655.75
   373.8 2659.63     439 2693.28   455.5  2704.1   467.2 2710.39   552.7 2752.21
#Mann= 3, -1 ,  0
       0     0.1       0   302.1   0.045       0   324.6     0.1       0
Bank Sta=302.1,324.6
XS Rating Curve= 0 ,0
Exp/Cntr(USF)=0,0
Exp/Cntr=0.3,0.1

Type RM Length L Ch R = 1 ,7041    ,37.4,37.6,37.3
XS GIS Cut Line= 2
2378977.69226487712641.9706723392379441.80127754712465.416961303
#Sta/Elev= 30
       0 2748.15    24.2 2733.18    45.5 2722.08    64.5 2709.99    75.4 2706.42
    89.3 2698.04   101.1 2693.22   154.5  2667.4   176.2 2655.53   188.6 2650.36
   195.2 2646.28   213.4 2640.38   233.8 2631.45   255.2  2620.2   280.8 2617.72
   306.5 2618.54  319.16 2618.54     325  2620.1   331.2 2623.51   353.6 2641.38
   366.4 2653.52     375  2659.4   387.8 2671.27   392.1 2674.25   400.7 2678.47
   427.3 2695.77   443.5 2708.29   452.1 2711.97   464.9 2723.29   496.6 2737.19
#Mann= 3, -1 ,  0
       0     0.1       0   306.5   0.045       0  319.16     0.1       0
Bank Sta=306.5,319.16
XS Rating Curve= 0 ,0
Exp/Cntr(USF)=0,0
Exp/Cntr=0.3,0.1

Type RM Length L Ch R = 1 ,7004    ,128,128.4,126.7
XS GIS Cut Line= 2
2378989.44672258712679.2314657042379454.36955002 712499.39025738
#Sta/Elev= 30
       0 2747.66    28.7 2729.01    65.5 2707.68      93 2695.94   118.1 2682.81
   135.9 2676.04   170.2 2658.28   189.3 2649.85   200.2 2643.28   217.4 2639.12
   238.8 2628.14   254.2  2618.6   272.7  2614.8   294.6  2616.5   309.9 2614.44
   315.9 2613.94  322.69 2614.43   333.2 2615.79   337.5 2618.15   359.3  2642.8
   371.8 2652.91   380.3  2662.3   384.6 2668.48   388.9 2672.11   402.6 2681.38
   418.9 2689.62   431.8 2698.21     449 2707.13   482.4 2727.48   498.5 2733.99
#Mann= 3, -1 ,  0
       0     0.1       0   309.9   0.045       0  322.69     0.1       0
Bank Sta=309.9,322.69
XS Rating Curve= 0 ,0
Exp/Cntr(USF)=0,0
Exp/Cntr=0.3,0.1

Type RM Length L Ch R = 1 ,6875    ,125.2,122.3,118.6
XS GIS Cut Line= 2
2379110.00694001712803.7881544322379490.33779169712589.310861542
#Sta/Elev= 30
       0 2714.91    20.9 2702.66    56.4 2684.89    71.4 2679.04    85.1 2671.93
     103 2661.02     118 2653.74   126.5 2650.93     154 2635.97   163.2  2634.5
   167.8 2632.58   181.6 2623.67   195.4  2621.4   209.1 2614.88   218.3 2608.36
   232.5 2609.58   245.9 2607.44  263.14 2608.03  269.89 2608.04   273.4 2609.53
   291.3 2624.41   305.9 2638.25   314.8 2641.53   328.5 2651.83   339.2 2657.61
   367.6 2675.89   397.4 2689.63   411.2 2698.36   420.5    2702   436.6 2712.04
#Mann= 3, -1 ,  0
       0     0.1       0  263.14   0.045       0  269.89     0.1       0
Bank Sta=263.14,269.89
XS Rating Curve= 0 ,0
Exp/Cntr(USF)=0,0
Exp/Cntr=0.3,0.1

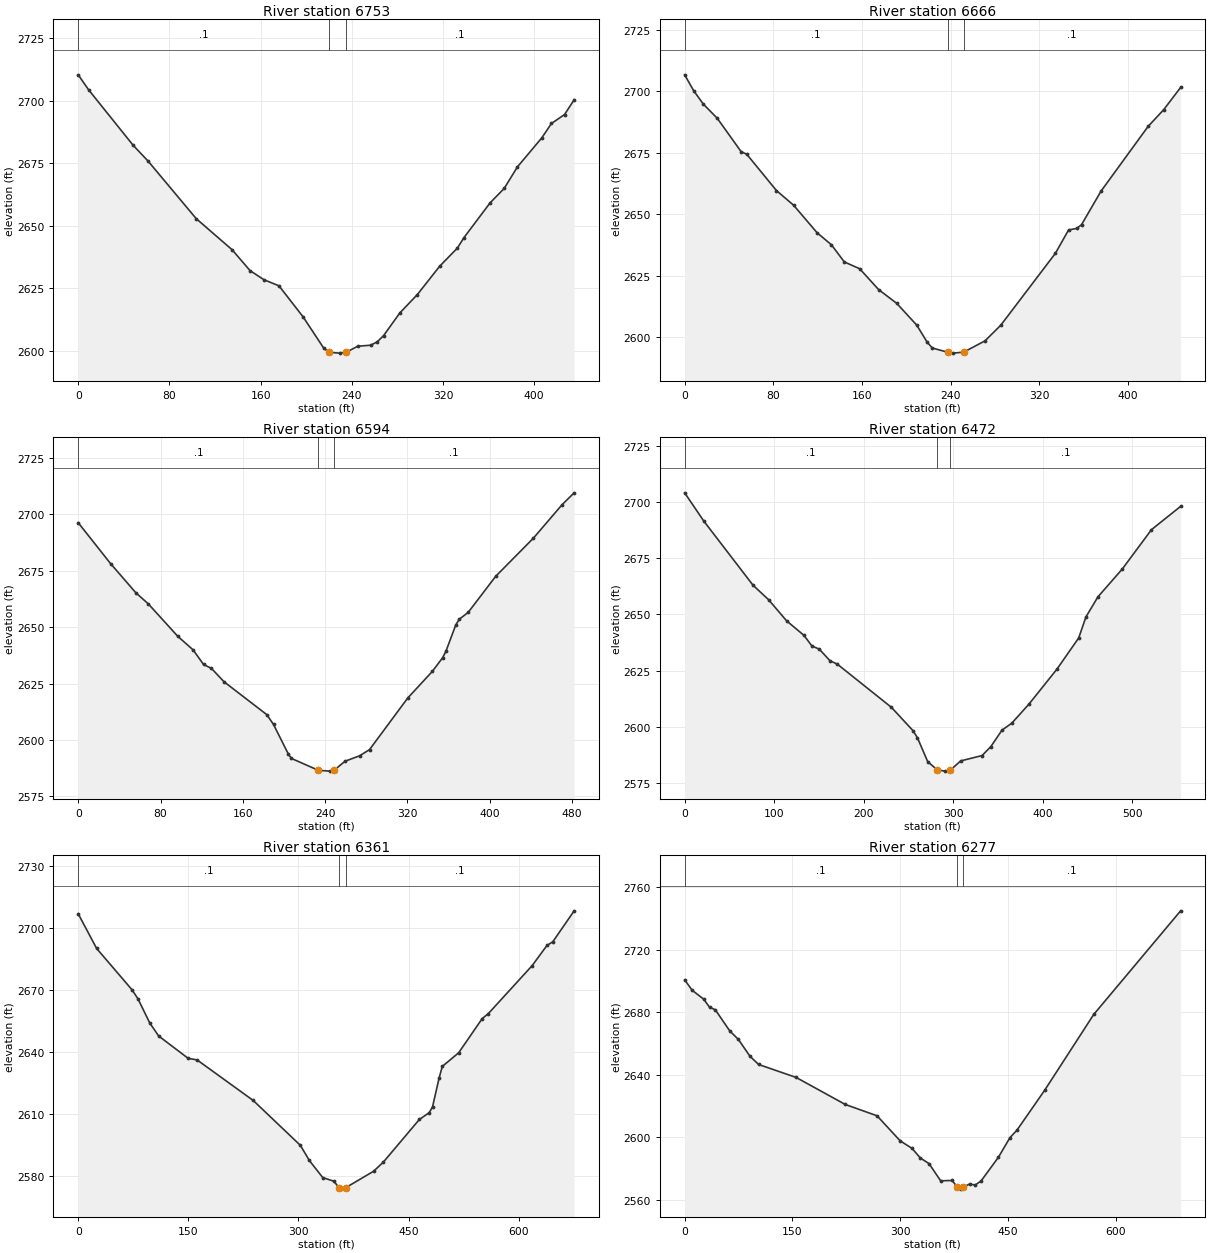
Type RM Length L Ch R = 1 ,6753    ,85.3,86.8,88.3
XS GIS Cut Line= 3
2379168.62185235712889.0462087482379333.80933259712811.781097024
2379518.31309076712639.266752743
#Sta/Elev= 30
       0 2710.35     9.1 2704.38    48.1 2682.22    61.3 2675.85   103.5 2652.84
     135  2640.4   150.7 2632.07   162.9 2628.42   176.1 2625.97   197.2  2613.6
   215.5 2600.95  220.38 2599.36   229.4 2599.06   234.9 2599.39   245.3 2601.83
   256.5 2602.22   262.3 2603.59   267.9 2606.09   282.1 2615.13   297.5  2622.5
     317 2633.79   332.6 2641.08   338.4 2645.28   361.3 2659.17   373.6  2664.9
   385.3 2673.57   406.6 2685.13   415.1  2690.9   426.6 2694.48     435 2700.39
#Mann= 3, -1 ,  0
       0     0.1       0  220.38   0.045       0   234.9     0.1       0
Bank Sta=220.38,234.9
XS Rating Curve= 0 ,0
Exp/Cntr(USF)=0,0
Exp/Cntr=0.3,0.1

Type RM Length L Ch R = 1 ,6666    ,72.5,72.3,72.5
XS GIS Cut Line= 4
2379208.58656531 712928.344843162379403.08150172712854.410124182
2379457.69994277712821.106196715 2379576.9280031712692.553036691
#Sta/Elev= 30
       0 2706.68     8.1 2700.25    16.7 2694.86    29.5 2688.97    50.9 2675.49
      56 2674.42    82.8 2659.67    98.3  2653.7   119.4 2642.56   132.4 2637.63
     144 2630.68   157.9  2627.9     175 2619.42   191.3 2613.85   209.4 2604.98
   218.7 2598.11   223.4 2595.71   237.12594.017   242.1 2593.63  251.76 2594.04
   270.9 2598.61   285.1 2604.93   334.5 2634.22   346.3 2643.64   353.8 2644.32
     358 2645.81   375.6 2659.43   418.1 2685.74   432.2 2692.55   447.4 2701.56
#Mann= 3, -1 ,  0
       0     0.1       0   237.1   0.045       0  251.76     0.1       0
Bank Sta=237.1,251.76
XS Rating Curve= 0 ,0
Exp/Cntr(USF)=0,0
Exp/Cntr=0.3,0.1

Type RM Length L Ch R = 1 ,6594    ,123,121.6,119.2
XS GIS Cut Line= 4
2379253.40474628712962.3853662642379420.33554321712927.847960002
2379551.08429549712848.0829979212379613.58055444712702.532500104
#Sta/Elev= 30
       0 2696.31    31.4 2678.21    55.9 2665.31    68.2 2660.29    96.8 2645.93
   111.7 2639.92   121.8 2633.47   129.5 2631.72   141.7 2625.81   183.3 2611.22
   189.8 2606.88   204.3 2593.69   207.2 2591.82   233.4 2586.56   244.7 2586.19
  248.69 2586.57   259.3 2590.57   273.4 2592.97   283.1 2595.71   320.2 2618.56
   344.2 2630.41   354.1 2636.41   357.3 2639.23   366.9 2650.93   370.3  2653.5
     379 2656.55   405.8 2672.57   442.4 2689.46   470.4 2704.36     482 2709.55
#Mann= 3, -1 ,  0
       0     0.1       0   233.4   0.045       0  248.69     0.1       0
Bank Sta=233.4,248.69
XS Rating Curve= 0 ,0
Exp/Cntr(USF)=0,0
Exp/Cntr=0.3,0.1

Type RM Length L Ch R = 1 ,6472    ,109.9,111.2,112.6
XS GIS Cut Line= 4
2379275.19442025713046.240746395 2379529.6364261713011.604661828
2379619.55703026 712918.353664922379650.19664353712753.166184681
#Sta/Elev= 30
       0 2704.02    21.2 2691.56    76.4 2662.95    93.8 2656.52     114  2647.1
   133.3 2640.69   142.3 2635.91   150.4 2634.57   162.5 2629.35   170.5 2627.92
   231.1 2608.68   255.3 2598.28   260.2 2595.12   271.6 2584.58   282.4 2580.84
   291.4 2580.34   297.1 2580.82   308.4 2584.87   332.4 2587.27   342.3 2591.28
   354.6 2598.53   365.7 2601.68   384.8 2610.13     416 2625.62   440.4 2639.54
   448.5 2648.88   461.9  2657.8   489.2 2670.21   521.7 2687.64   554.3 2698.01
#Mann= 3, -1 ,  0
       0     0.1       0   282.4   0.045       0   297.1     0.1       0
Bank Sta=282.4,297.1
XS Rating Curve= 0 ,0
Exp/Cntr(USF)=0,0
Exp/Cntr=0.3,0.1

Type RM Length L Ch R = 1 ,6361    ,82.3,84.3,84.9
XS GIS Cut Line= 4
2379279.19089154713111.5164442312379604.23722362713077.546438214
2379777.41764646712992.954462447  2379933.280027712998.949169391
#Sta/Elev= 30
       0 2706.98    25.1 2690.21    73.4 2670.15    81.4 2665.81    97.5  2654.1
   109.6 2647.83   149.8 2637.01   161.9 2636.26   238.3 2616.64   302.6  2594.9
   314.7 2587.64     333 2579.31     348 2577.57  355.61 2574.33   357.9 2573.71
   364.1 2574.35   402.4 2582.38   415.8 2586.86   464.7 2607.45   478.1 2610.71
   482.6 2613.53   491.5 2627.39   495.9 2633.11   518.2  2639.7   550.3 2656.28
   558.3 2658.55   618.4 2681.94   638.4 2691.64   646.4 2693.44   675.5 2708.42
#Mann= 3, -1 ,  0
       0     0.1       0  355.61   0.045       0   364.1     0.1       0
Bank Sta=355.61,364.1
XS Rating Curve= 0 ,0
Exp/Cntr(USF)=0,0
Exp/Cntr=0.3,0.1

Type RM Length L Ch R = 1 ,6277    ,14.1,14.2,14.7
XS GIS Cut Line= 2
2379293.78560741713173.2256554742379980.51259179713103.953486341
#Sta/Elev= 30
       0 2700.67    10.4 2694.02    26.5  2688.3    34.6 2683.16    42.6 2681.54
    62.7 2668.02    74.8 2662.53    90.8 2651.81   102.9 2646.52   155.2 2638.21
   223.5 2620.93   267.7 2613.69   299.9 2597.65   316.3 2592.87     328 2586.67
   340.1 2583.07   356.2 2572.09   372.3 2572.28   379.62567.884   384.3 2566.75
   387.2  2567.9   396.4 2569.99   404.4 2569.42   412.5 2571.98   436.6 2587.12
   452.7 2599.72   462.4 2604.47   500.9 2629.95   569.3 2678.55   690.2 2744.85
#Mann= 3, -1 ,  0
       0     0.1       0   379.6   0.045       0   387.2     0.1       0
Bank Sta=379.6,387.2
XS Rating Curve= 0 ,0
Exp/Cntr(USF)=0,0
Exp/Cntr=0.3,0.1

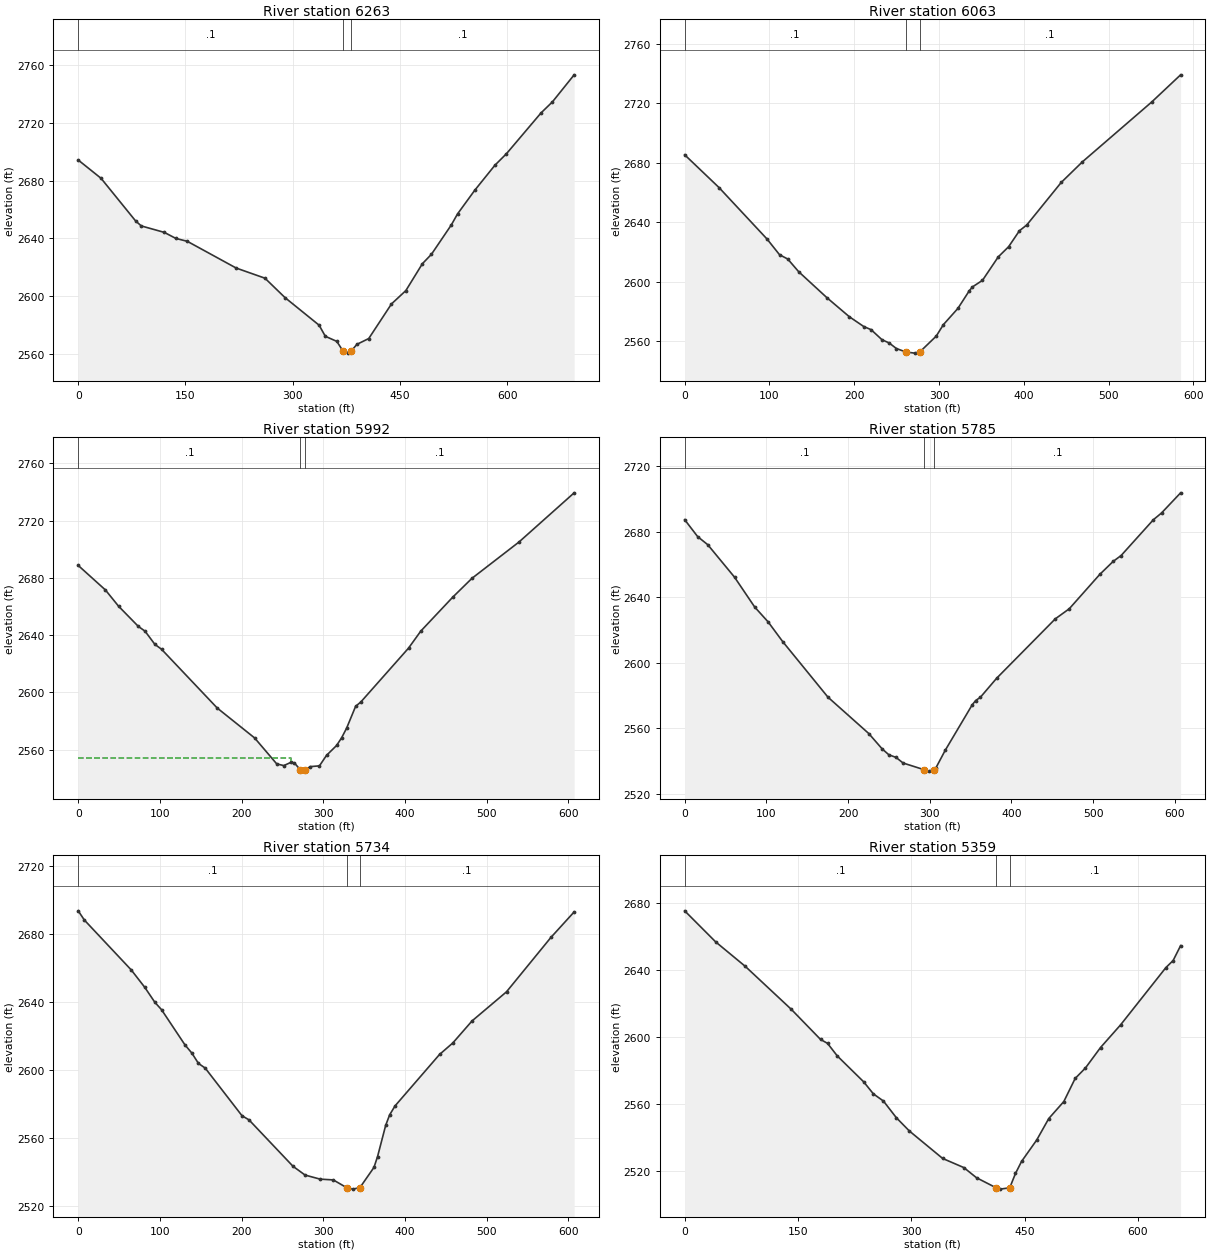
Type RM Length L Ch R = 1 ,6263    ,201.4,199.4,197.3
XS GIS Cut Line= 2
2379304.38853648713186.0561877692379994.31434251713116.981375245
#Sta/Elev= 30
       0 2694.28    31.9 2681.61    80.2 2652.06    88.2 2648.57   120.4 2644.09
   136.5 2639.91   152.5 2637.91   220.9 2619.36   261.1 2612.33   289.2 2598.84
   336.8 2579.75   345.5 2572.05   361.6  2568.5     370 2561.97   377.7 2560.37
   381.92561.963   389.7 2566.47   406.2 2570.48     438 2594.48   458.1 2603.74
   481.2 2622.36   493.9 2628.93   521.5 2649.14   530.4 2656.93   554.5 2673.35
   582.7 2690.71   598.8 2698.67     647 2726.88   663.1 2734.64   693.4 2753.35
#Mann= 3, -1 ,  0
       0     0.1       0     370   0.045       0   381.9     0.1       0
Bank Sta=370,381.9
XS Rating Curve= 0 ,0
Exp/Cntr(USF)=0,0
Exp/Cntr=0.3,0.1

Type RM Length L Ch R = 1 ,6063    ,70.9,71.1,71.4
XS GIS Cut Line= 3
2379458.21761413713439.1676116782379848.29319499713293.496232935
2379993.42505011713207.711976565
#Sta/Elev= 30
       0 2685.34    40.5  2663.3    97.2 2628.64   111.9 2618.11   121.6 2615.21
   134.5 2606.67   167.8  2589.2   194.2 2576.41   211.3 2569.79   219.9  2567.7
   232.7 2560.96   241.2 2558.75   249.7 2555.03  260.632552.734   271.1 2551.92
   277.42552.743   296.7 2563.34   305.2 2571.11   322.3 2582.01   335.7 2593.85
   339.4 2596.44   351.3  2600.9   369.9 2616.67   382.1 2623.49   394.9 2634.27
   403.5  2638.1   444.1  2666.7   469.1 2680.57   550.9 2720.85     585 2739.13
#Mann= 3, -1 ,  0
       0     0.1       0  260.63   0.045       0   277.4     0.1       0
Bank Sta=260.63,277.4
XS Rating Curve= 0 ,0
Exp/Cntr(USF)=0,0
Exp/Cntr=0.3,0.1

Type RM Length L Ch R = 1 ,5992    ,208.6,207.7,206.6
XS GIS Cut Line= 4
2379463.25861419713473.7007084162379653.89228257713445.500461615
2379779.10137836713391.3559877582380018.23947123713249.226743883
#Sta/Elev= 30
       0 2688.71    33.3 2671.59    49.4 2660.24    73.7 2646.08    81.8 2642.81
    93.9 2633.57     102 2630.18   170.3 2589.06     216 2568.21   243.1 2550.07
   251.8 2548.89   260.6 2551.19   264.7 2550.77  272.06 2545.88   273.8 2545.02
     278 2545.89   284.2 2548.17   295.4 2548.71   304.1 2556.06   316.4 2562.94
   322.5 2568.26   328.6 2574.94   339.7 2590.29   346.1 2593.34   404.5 2630.95
   419.5 2642.84   458.6 2666.53   482.1 2679.68   539.8  2705.1   607.3 2739.44
#Mann= 3, -1 ,  0
       0     0.1       0  272.06   0.045       0     278     0.1       0
#XS Ineff= 2 , 0
          260.86 2553.92
Permanent Ineff=
       F       F
Bank Sta=272.06,278
XS Rating Curve= 0 ,0
Exp/Cntr(USF)=0,0
Exp/Cntr=0.3,0.1

Type RM Length L Ch R = 1 ,5785    ,49.7,50.4,50.5
XS GIS Cut Line= 3
2379548.71886131713672.2825488772379800.34853551713613.897885909
2380083.22633918713409.962725121
#Sta/Elev= 30
       0 2687.23    15.9 2676.88    28.2 2671.97      61 2652.13    85.7 2633.88
   102.2 2624.77   119.9 2612.82   175.4 2578.82   225.3 2556.64   241.7 2547.25
   249.9 2543.65   258.7 2542.05   267.3 2538.63   293.1 2534.53   298.8 2533.67
  305.14 2534.51   307.4 2535.58   318.9  2546.4   351.8 2574.06   356.1 2576.77
   361.9 2578.76   381.9 2590.43   453.6 2626.66   470.7 2632.82     508 2653.78
   524.4 2661.73   534.2 2665.35   573.7 2687.22   583.6  2691.3     607 2703.63
#Mann= 3, -1 ,  0
       0     0.1       0   293.1   0.045       0  305.14     0.1       0
Bank Sta=293.1,305.14
XS Rating Curve= 0 ,0
Exp/Cntr(USF)=0,0
Exp/Cntr=0.3,0.1

Type RM Length L Ch R = 1 ,5734    ,371.7,375.2,380.7
XS GIS Cut Line= 3
2379552.83045729713728.6114138522379804.46013149713670.226750885
2380087.33793516713466.291590097
#Sta/Elev= 30
       0 2693.78     7.5 2688.36      65 2658.88    81.5 2648.65    93.8 2639.85
     102 2635.48   130.7 2614.71     139 2609.96   147.2  2603.8   155.4 2601.07
   200.5 2572.95     209 2570.54   262.9 2543.15   277.7 2537.97   296.1 2535.58
   312.2 2535.12   328.5 2530.58   336.2 2529.69   344.8 2530.59     362 2542.51
   366.4 2548.92   376.3 2567.26   381.2 2573.51   387.8 2578.77   442.2 2609.07
   458.5 2615.88   482.1 2628.89   524.2 2646.03   578.5 2678.06     607 2693.14
#Mann= 3, -1 ,  0
       0     0.1       0   328.5   0.045       0   344.8     0.1       0
Bank Sta=328.5,344.8
XS Rating Curve= 0 ,0
Exp/Cntr(USF)=0,0
Exp/Cntr=0.3,0.1

Type RM Length L Ch R = 1 ,5359    ,403.1,407.2,412
XS GIS Cut Line= 4
2379566.57453091713882.4422316792379833.37142584713997.566919218
2380024.33221707 713982.034223282380164.12648051713877.873791697
#Sta/Elev= 30
       0  2675.6      41 2657.04    80.2 2642.41   141.2 2616.68   179.8 2598.73
   189.1 2596.36   202.1  2588.8     237 2573.34   249.8 2566.15   263.1 2561.88
   280.2  2551.9   297.4 2543.98   341.5 2527.55   369.6 2522.08   386.3 2516.02
   412.3 2510.01   417.8 2509.21  430.292510.024   437.9 2518.57   445.9 2525.74
     466 2538.58     482 2551.43   501.9 2561.58   516.9 2575.38   530.5 2581.63
   550.5 2593.88     577  2607.4     637 2641.66   646.6  2645.9   656.5  2654.8
#Mann= 3, -1 ,  0
       0     0.1       0   412.3   0.045       0  430.29     0.1       0
Bank Sta=412.3,430.29
XS Rating Curve= 0 ,0
Exp/Cntr(USF)=0,0
Exp/Cntr=0.3,0.1

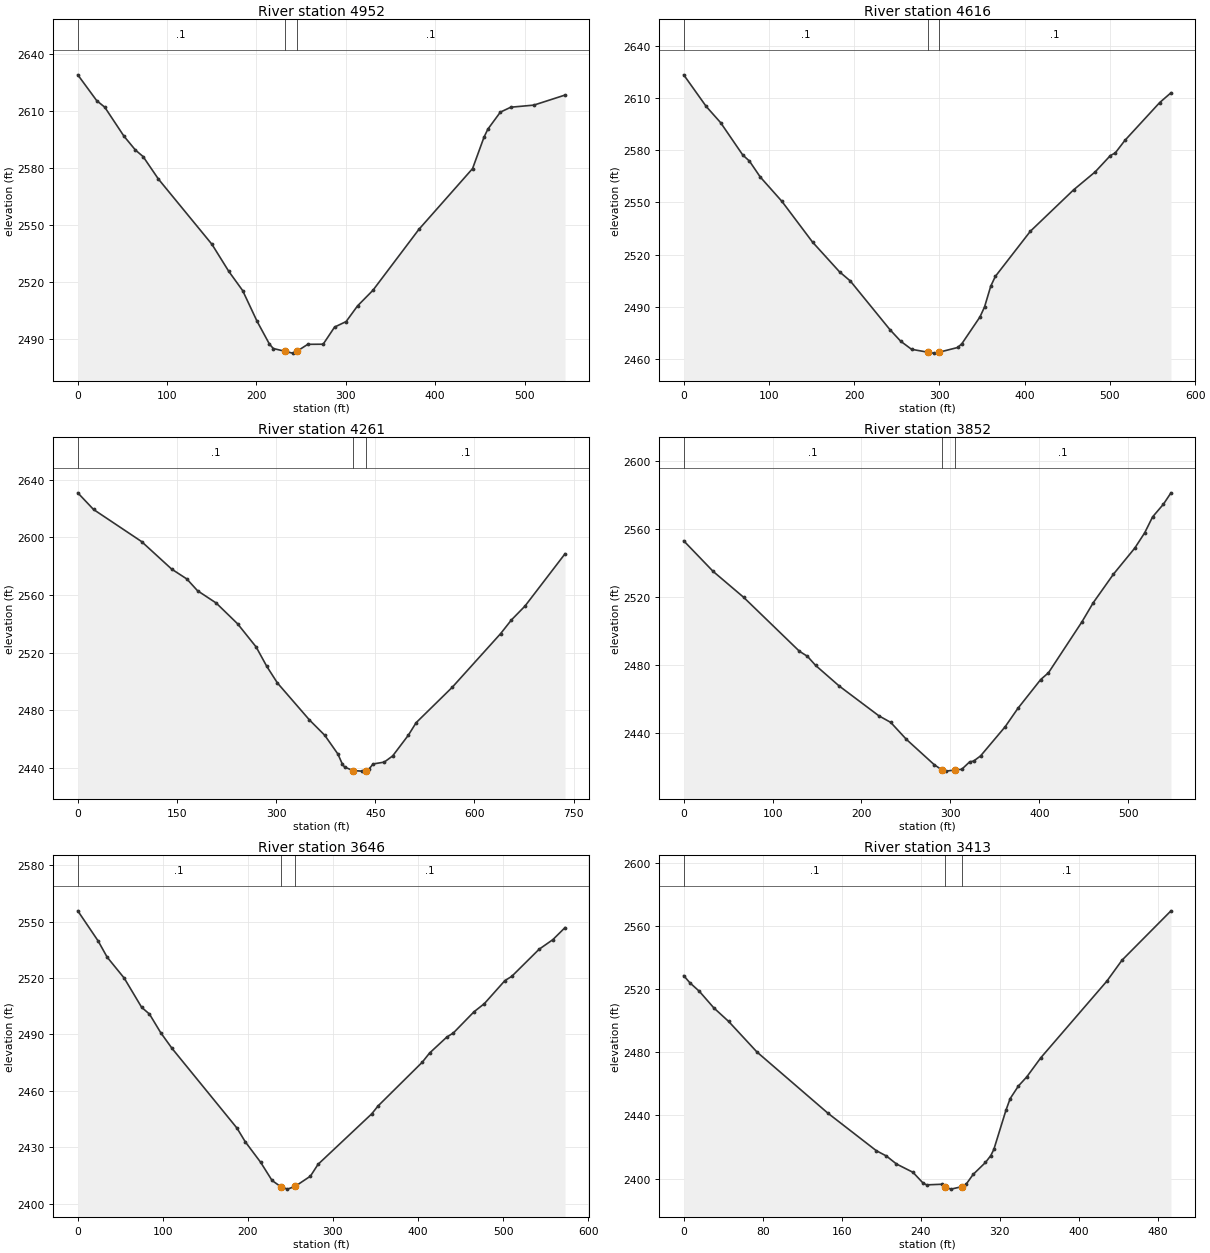
Type RM Length L Ch R = 1 ,4952    ,337.9,335.4,328.8
XS GIS Cut Line= 2
2379528.02100817 714217.889643892380036.75346046714414.163361628
#Sta/Elev= 30
       0 2628.87    21.2 2615.29    30.2 2611.86    51.6 2596.68    64.5 2589.34
    73.1 2585.91    90.2 2574.11   150.2 2539.75     169 2525.56   184.5 2515.48
   200.7 2499.27   214.5 2487.33   218.8 2485.02   231.4  2483.6   240.3 2482.59
  245.142483.536   257.4 2487.22   274.6 2487.28   287.4 2496.29   300.3 2499.18
   313.1 2507.43   330.3 2515.62   381.7 2547.62   441.8 2579.58   454.6 2596.09
   458.9 2600.31   472.9 2609.26   484.6 2611.85   510.4 2612.95   545.3 2618.24
#Mann= 3, -1 ,  0
       0     0.1       0   231.4   0.045       0  245.14     0.1       0
Bank Sta=231.4,245.14
XS Rating Curve= 0 ,0
Exp/Cntr(USF)=0,0
Exp/Cntr=0.3,0.1

Type RM Length L Ch R = 1 ,4616    ,357,355.1,351.7
XS GIS Cut Line= 3
2379539.16389102714712.0709323582380008.79952114714552.175532998
2380063.62080092714500.095317206
#Sta/Elev= 30
       0 2623.63    26.4 2605.39    43.3 2596.06    69.3 2577.38    77.1  2573.9
    89.8 2564.71   115.2 2550.67   151.2 2527.13   182.8 2510.02   195.4 2504.77
   241.9  2476.7   254.6 2469.98   267.3 2465.33   286.8 2463.61   293.1 2463.12
   299.4 2463.61   321.5 2466.38   326.4  2468.6   347.6    2484     353 2489.82
   360.2 2501.69   365.6 2507.35   406.7 2533.41   457.4 2557.27   482.8 2567.67
   500.6 2577.08   506.3 2578.56   517.6  2585.8   558.5 2607.66   571.7 2613.27
#Mann= 3, -1 ,  0
       0     0.1       0   286.8   0.045       0   299.4     0.1       0
Bank Sta=286.8,299.4
XS Rating Curve= 0 ,0
Exp/Cntr(USF)=0,0
Exp/Cntr=0.3,0.1

Type RM Length L Ch R = 1 ,4261    ,397.9,409.5,419.2
XS GIS Cut Line= 4
2379576.52543266714905.9756658432379942.00063121714952.224070597
2380042.39350982714876.6474091692380279.27558295714822.502935311
#Sta/Elev= 30
       0 2631.01    23.8 2619.46    96.4 2597.19   142.1 2577.99     165 2571.16
   181.1 2563.02   209.3 2554.48   241.6  2540.1   269.8 2523.92   285.9 2510.44
     302  2498.9   350.4 2473.24   373.5 2462.62   393.4 2449.59   400.1 2442.66
   403.5 2440.54   416.2 2438.08   429.2 2437.69  436.09 2438.08   440.7 2439.25
   446.6 2442.65   463.5 2443.95   476.3 2448.26     500 2462.66   511.8 2471.36
   566.3  2495.9   639.5 2533.18   655.9 2542.72   676.4 2552.35     737 2588.69
#Mann= 3, -1 ,  0
       0     0.1       0   416.2   0.045       0  436.09     0.1       0
Bank Sta=416.2,436.09
XS Rating Curve= 0 ,0
Exp/Cntr(USF)=0,0
Exp/Cntr=0.3,0.1

Type RM Length L Ch R = 1 ,3852    ,205,205.2,205.2
XS GIS Cut Line= 3
2379638.34427182715097.2242631122380053.53323423715297.047827912
2380140.86353292 715292.60730425
#Sta/Elev= 30
       0 2553.07    33.1 2535.07    67.3 2519.88   130.2 2488.05   139.2 2485.08
   148.5 2479.68   175.1 2467.54   219.6 2450.05   232.9 2446.19   250.6 2436.16
   281.7 2421.36   290.6 2418.16     295  2417.5  305.32 2418.17   312.8 2418.57
   321.7 2422.96   326.1  2423.4     334 2426.47   361.6  2443.6   375.9  2454.4
   401.6  2471.4   410.4 2475.42   447.9 2505.27   460.8 2516.68   483.4 2533.39
   507.5 2548.81   518.6 2557.77   527.5 2567.14   539.7 2574.64   548.2 2581.32
#Mann= 3, -1 ,  0
       0     0.1       0   290.6   0.045       0  305.32     0.1       0
Bank Sta=290.6,305.32
XS Rating Curve= 0 ,0
Exp/Cntr(USF)=0,0
Exp/Cntr=0.3,0.1

Type RM Length L Ch R = 1 ,3646    ,233.9,233.3,232.3
XS GIS Cut Line= 3
2379573.56589159715282.1513417622379942.08671679715474.025820999
2380098.42888506715492.299580926
#Sta/Elev= 30
       0 2555.76    23.9 2539.75    34.5 2531.14    54.6 2519.96    75.1 2504.42
    84.3 2500.82    97.6 2490.86   110.9 2482.52   187.2 2440.14   196.9 2432.89
   214.9 2422.03   228.4  2412.3   238.5 2409.04   246.5 2407.69   255.5 2409.14
   273.5 2414.59   282.5 2420.89   345.7 2447.79     353 2451.92     405 2475.21
   413.6 2480.09   433.7 2488.52   441.7 2490.84   465.9 2502.07     478 2506.37
   502.2 2518.65   510.2 2520.88   542.4 2535.32   558.5 2540.41   572.9 2546.85
#Mann= 3, -1 ,  0
       0     0.1       0   238.5   0.045       0   255.5     0.1       0
Bank Sta=238.5,255.5
XS Rating Curve= 0 ,0
Exp/Cntr(USF)=0,0
Exp/Cntr=0.3,0.1

Type RM Length L Ch R = 1 ,3413    ,154.2,154.6,154.4
XS GIS Cut Line= 4
2379531.03161665715479.1092980632379708.65256313715601.223698774
 2379806.3440837715638.9681499032379971.38354648715691.514346573
#Sta/Elev= 30
       0  2528.5     6.2 2524.02    15.9 2518.55    30.5 2508.09    45.5 2499.52
    74.2 2480.14   146.1 2441.38     195 2417.69   205.3 2414.28   215.5 2409.23
   232.2 2403.96   242.7 2396.96   246.1 2396.01   261.5  2396.4   264.6  2394.8
   270.8 2393.31     282 2394.91   286.3 2396.65   293.1  2402.6   305.6 2410.19
     311 2414.55   314.1 2418.46   326.4 2443.35   330.6 2450.61     339 2458.65
   347.4 2464.36   361.7 2476.54   428.6 2525.07   443.9  2538.3   493.5 2569.56
#Mann= 3, -1 ,  0
       0     0.1       0   264.6   0.045       0     282     0.1       0
Bank Sta=264.6,282
XS Rating Curve= 0 ,0
Exp/Cntr(USF)=0,0
Exp/Cntr=0.3,0.1

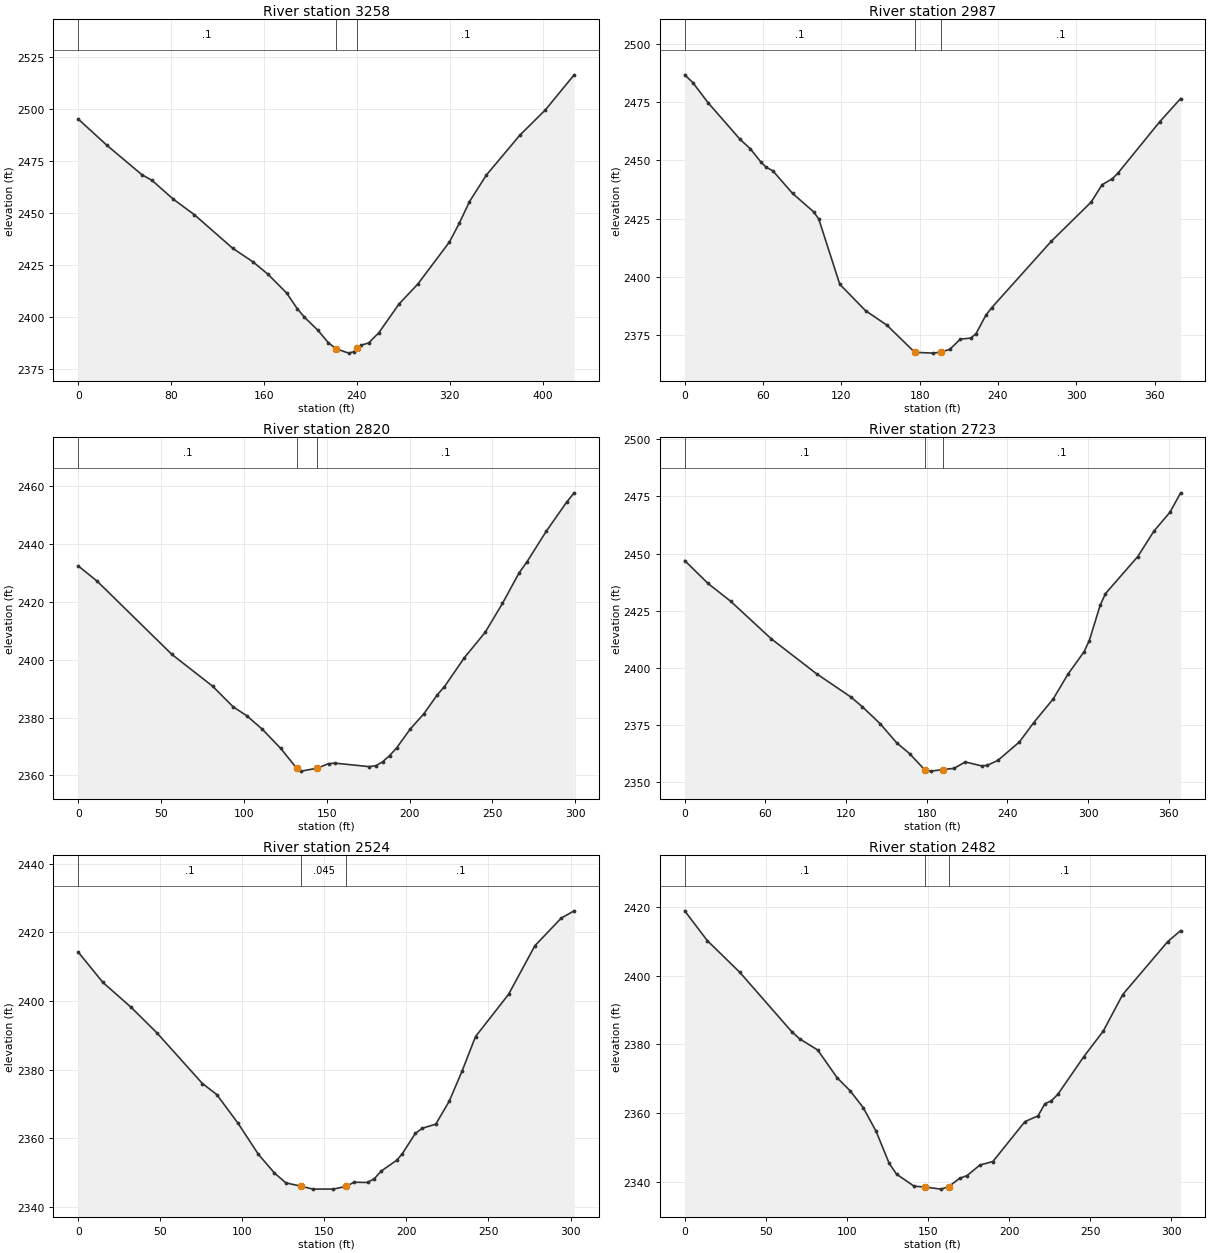
Type RM Length L Ch R = 1 ,3258    ,273.3,271.1,267.7
XS GIS Cut Line= 2
2379453.57235661715652.7182011432379847.24780196715818.535652334
#Sta/Elev= 30
       0 2495.25    24.5 2482.73    54.9 2468.45    63.6 2465.74    81.7 2456.79
   100.1  2449.2     133 2433.11   150.4  2426.6   163.4 2420.62   179.5 2411.58
   188.6 2404.09   194.7 2400.01   206.5  2393.6   215.5 2387.62  222.052384.791
   232.9 2382.63   237.2 2383.28   240.42384.876   243.6 2386.42   250.2 2387.53
   258.9  2392.4   276.3 2406.24   292.5 2415.84   319.7 2436.05   328.3 2445.15
     337 2455.49   351.5 2468.25   380.4 2487.47   402.4 2499.64   427.2 2516.52
#Mann= 3, -1 ,  0
       0     0.1       0  222.05   0.045       0   240.4     0.1       0
Bank Sta=222.05,240.4
XS Rating Curve= 0 ,0
Exp/Cntr(USF)=0,0
Exp/Cntr=0.3,0.1

Type RM Length L Ch R = 1 ,2987    ,165.7,167.3,167.2
XS GIS Cut Line= 2
2379405.95686683715975.7078609552379784.14146539 716011.97213753
#Sta/Elev= 30
       0 2486.69     6.2 2483.39      18 2474.68    42.4 2459.04    50.4 2454.91
    58.5 2449.21    62.5 2447.02    67.5 2445.56    82.6 2435.87    98.7 2427.96
   102.7 2424.88   118.8 2396.86   138.6 2385.53   154.9 2379.34   176.22367.708
   190.4 2367.34   196.4 2367.82   203.1 2368.98   211.2 2373.36   219.2 2373.79
   223.2 2375.71   230.7 2383.58   235.3  2386.9   280.8  2415.3   311.4 2432.13
   319.7 2439.53   327.7  2442.2   331.7 2444.42   363.9 2466.58   379.9 2476.51
#Mann= 3, -1 ,  0
       0     0.1       0   176.2   0.045       0   196.4     0.1       0
Bank Sta=176.2,196.4
XS Rating Curve= 0 ,0
Exp/Cntr(USF)=0,0
Exp/Cntr=0.3,0.1

Type RM Length L Ch R = 1 ,2820    ,95.3,96.8,97
XS GIS Cut Line= 2
2379437.10657856716122.644536928 2379728.5976613716191.088575693
#Sta/Elev= 30
       0 2432.42    11.4 2427.16    56.6 2401.81    81.1 2390.87    93.5 2383.74
   101.8 2380.62   111.1 2375.99   122.3 2369.33   131.9  2362.5   134.6  2361.5
   144.4 2362.52   151.1 2364.09   155.2 2364.25   175.7 2363.05   179.8 2363.39
   183.9 2364.79     188 2366.88   192.2  2369.5   200.4 2376.01   208.6 2381.28
   216.8 2387.88   221.1  2390.7   233.2 2400.75   245.6 2409.41   256.1 2419.43
   266.1 2429.96   270.9  2433.8   282.5 2444.34   294.9 2454.48   299.4 2457.67
#Mann= 3, -1 ,  0
       0     0.1       0   131.9   0.045       0   144.4     0.1       0
Bank Sta=131.9,144.4
XS Rating Curve= 0 ,0
Exp/Cntr(USF)=0,0
Exp/Cntr=0.3,0.1

Type RM Length L Ch R = 1 ,2723    ,199.3,198.8,198.6
XS GIS Cut Line= 3
2379375.96239647716182.9392405242379574.50709045716255.235406269
2379732.04798894716253.077311769
#Sta/Elev= 30
       0 2446.92    17.3 2436.97    34.3 2429.09    64.3 2412.77    98.1 2397.43
   123.5 2387.32   132.2 2382.99   145.5 2375.53   157.7 2367.24   167.3 2362.52
  178.412355.512   183.3 2354.86   192.3 2355.57   200.3 2356.07   208.8 2358.87
     221 2357.13     225 2357.39     233 2359.57     249 2367.63   259.6 2376.05
   274.2 2386.49     285 2397.17     297 2406.98     301 2411.97     309 2427.29
     313 2432.47     337 2448.67   349.1 2459.86     361 2468.09   368.9 2476.55
#Mann= 3, -1 ,  0
       0     0.1       0  178.41   0.045       0   192.3     0.1       0
Bank Sta=178.41,192.3
XS Rating Curve= 0 ,0
Exp/Cntr(USF)=0,0
Exp/Cntr=0.3,0.1

Type RM Length L Ch R = 1 ,2524    ,45.2,42.9,41.6
XS GIS Cut Line= 4
2379354.38145147716384.1815526342379444.48189684716421.948206381
2379561.55852345716454.8591475042379643.89444257716445.462160039
#Sta/Elev= 30
       0 2414.25      15 2405.43    32.3 2398.13      48  2390.7    75.7 2375.95
    84.4 2372.76    97.4 2364.38   109.8 2355.34   119.5 2349.94   126.5 2347.03
   135.7 2346.06   143.1  2345.2   155.5 2345.23   163.42345.998     168 2347.21
   176.3 2347.14   180.5 2348.27   184.6 2350.45   194.1 2353.62   197.4 2355.45
   205.4 2361.41   209.6 2362.91   217.9 2364.14     226 2370.74     234 2379.69
   242.1 2389.64   262.2 2401.91   278.3 2416.11   294.4 2424.17   302.2 2426.26
#Mann= 3, -1 ,  0
       0     0.1       0   135.7   0.045       0   163.4     0.1       0
Bank Sta=135.7,163.4
XS Rating Curve= 0 ,0
Exp/Cntr(USF)=0,0
Exp/Cntr=0.3,0.1

Type RM Length L Ch R = 1 ,2482    ,299.1,301.3,302.4
XS GIS Cut Line= 2
2379326.21200284 716475.920318332379631.86804825716477.400492884
#Sta/Elev= 30
       0 2418.88      14 2410.18      34 2400.98      66  2383.7    70.9 2381.61
      82 2378.37      94 2370.28     102  2366.5     110 2361.63     118 2354.71
     126 2345.43   130.6 2342.24   141.4 2338.74   148.42338.479     158 2337.88
   162.82338.617   169.5 2341.03     174 2341.81     182 2344.89     190 2345.92
   209.7 2357.52   217.8 2359.21     222  2362.7     226  2363.6     230 2365.46
     246 2376.42     258 2383.87     270 2394.51   297.8 2409.95   305.7 2413.12
#Mann= 3, -1 ,  0
       0     0.1       0   148.4   0.045       0   162.8     0.1       0
Bank Sta=148.4,162.8
XS Rating Curve= 0 ,0
Exp/Cntr(USF)=0,0
Exp/Cntr=0.3,0.1