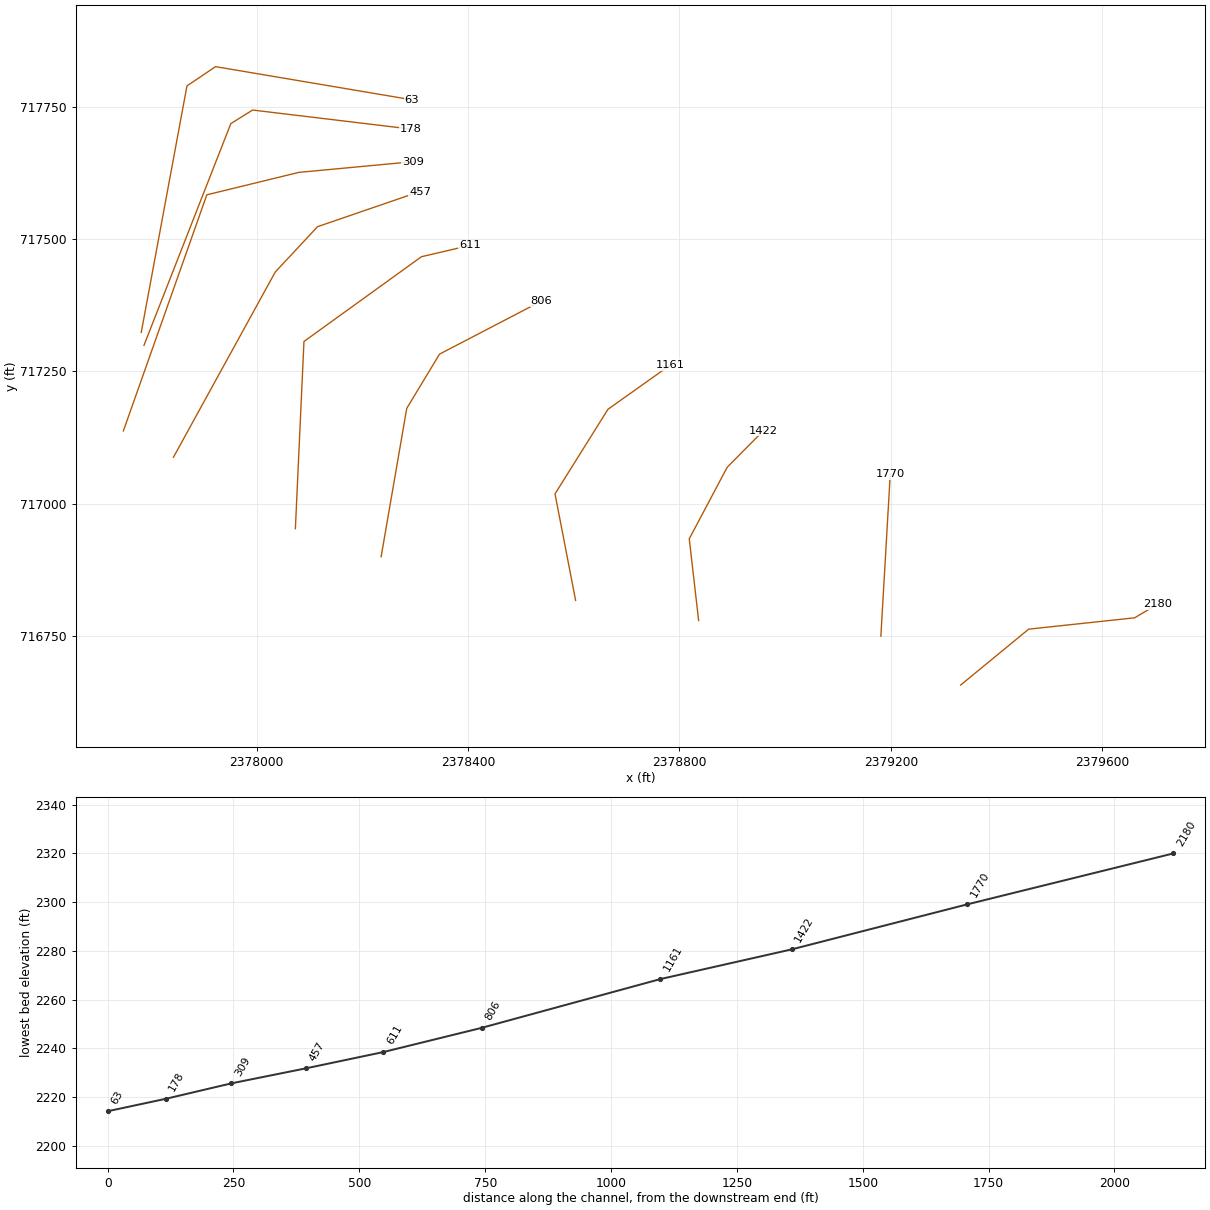
HEC-RAS study SNYDERRN.prj: SNYDERRN

--- SNYDERRN.g01 (geometry) --- (continued)

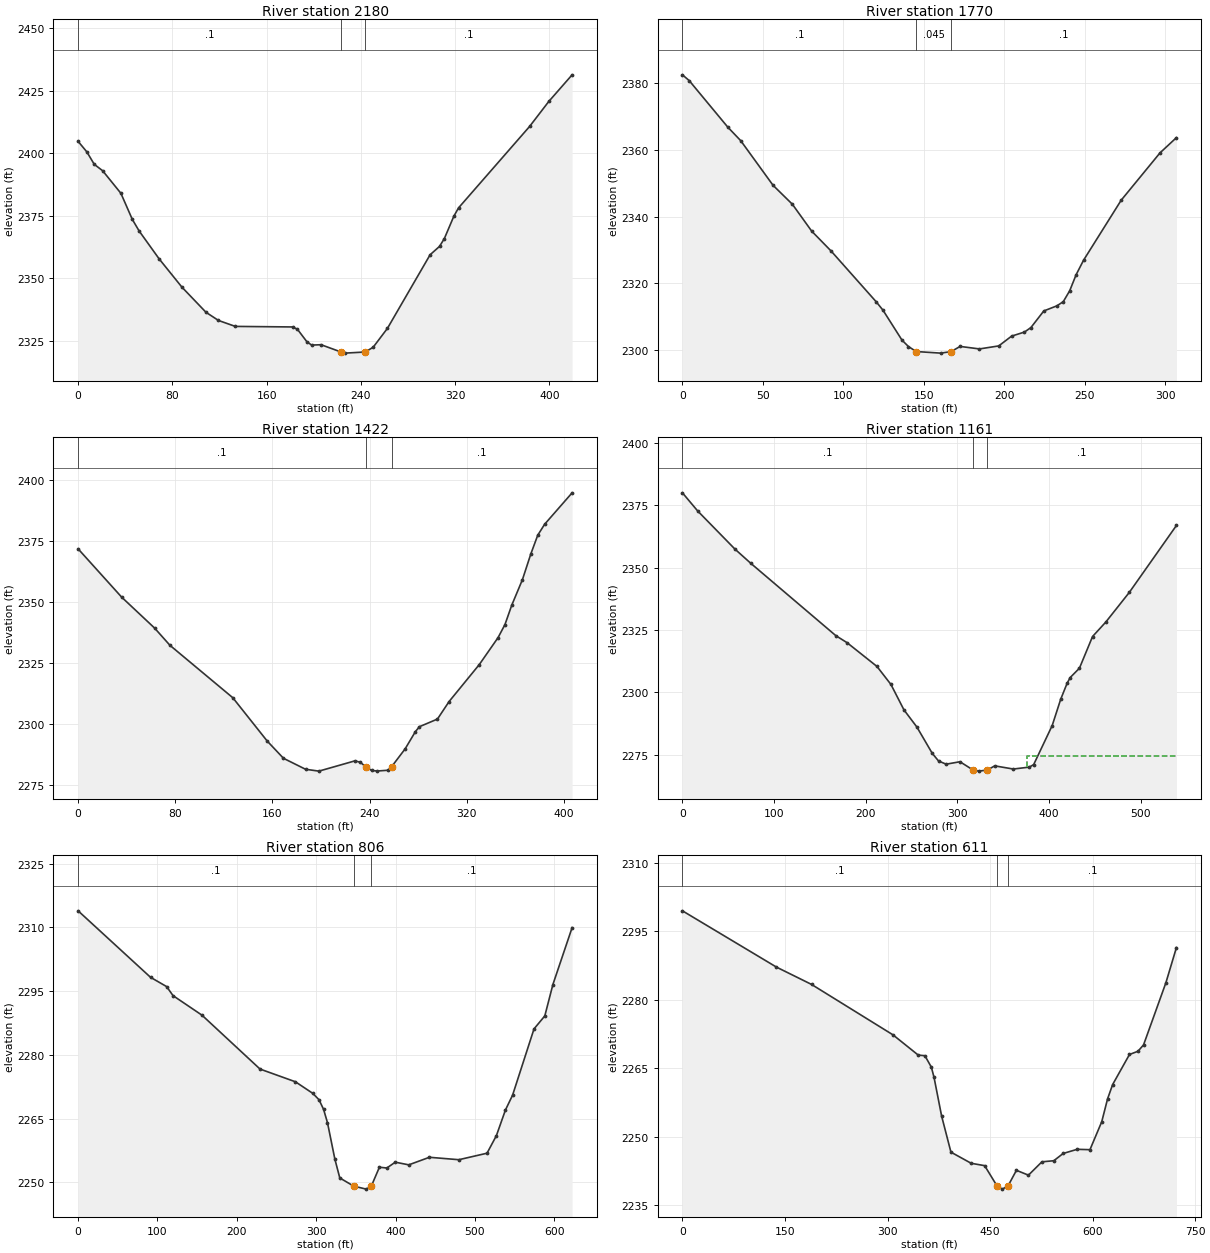
Type RM Length L Ch R = 1 ,2180    ,395,410.1,424.3
XS GIS Cut Line= 4
2379332.13270105716656.5016139272379460.90788726716762.334094543
2379661.47153933716783.7966255782379705.13668868716809.699680274
#Sta/Elev= 30
       0 2404.68     7.4 2400.48    13.7 2395.49    20.8 2392.94    36.3 2383.91
      46 2373.46    51.8 2368.82    68.7 2357.71    88.1 2346.36   108.5 2336.31
   119.1 2333.04   133.4 2330.66     182 2330.44   186.1 2329.52     194 2324.61
   198.1 2323.19   206.2 2323.33   223.1 2320.42   226.3 2319.97   243.7 2320.42
   250.4 2322.34   262.5 2329.89   298.7 2359.32   306.7 2362.67   310.8 2365.81
   318.8 2374.69   322.8 2378.06   383.1 2410.63   399.4 2420.64   419.2  2431.3
#Mann= 3, -1 ,  0
       0     0.1       0   223.1   0.045       0   243.7     0.1       0
Bank Sta=223.1,243.7
XS Rating Curve= 0 ,0
Exp/Cntr(USF)=0,0
Exp/Cntr=0.3,0.1

Type RM Length L Ch R = 1 ,1770    ,352.1,348.1,342.8
XS GIS Cut Line= 2
2379181.15489654716749.0125235572379198.91699119 717055.40865625
#Sta/Elev= 30
       0  2382.5     4.2 2380.77    28.2  2366.8    36.2 2362.76    56.3 2349.37
    68.3 2343.69    80.3 2335.63    92.3  2329.7   120.4 2314.43   124.6 2311.92
   136.4 2302.95   140.4 2301.03   145.2 2299.53   160.4 2299.05  166.952299.516
   172.5 2301.06   184.5 2300.31   196.5 2301.21   204.5 2304.15   212.5 2305.37
   216.5 2306.72   224.5  2311.7   232.6 2313.22   236.6 2314.48   240.6 2317.76
   244.6 2322.58   249.2 2326.91   272.6 2344.92   296.7  2359.1   306.9 2363.67
#Mann= 3, -1 ,  0
       0     0.1       0   145.2   0.045       0  166.95     0.1       0
Bank Sta=145.2,166.95
XS Rating Curve= 0 ,0
Exp/Cntr(USF)=0,0
Exp/Cntr=0.3,0.1

Type RM Length L Ch R = 1 ,1422    ,261.4,260.9,261
XS GIS Cut Line= 4
2378836.27422544716778.6160146382378818.51213079716933.294255539
2378890.30059666717068.7302272362378959.12871343717138.298431278
#Sta/Elev= 30
       0 2371.82    35.9 2351.98      63  2339.3    75.6 2332.25   127.4 2310.72
   155.7 2292.96   169.1 2285.88   187.3 2281.37   198.3 2280.61     228 2284.83
   232.5 2284.22   236.7 2282.42   241.6 2280.91   246.1 2280.65   255.2 2280.97
  258.112282.393   269.3 2289.75   277.8 2296.86   281.1 2298.85   295.9 2301.97
   305.5 2309.17   330.4 2324.36   345.8 2335.38   351.5 2340.75   357.1  2348.7
   365.9  2359.2   372.8 2369.72   378.5 2377.42   384.2 2381.93   406.8 2394.81
#Mann= 3, -1 ,  0
       0     0.1       0   236.7   0.045       0  258.11     0.1       0
Bank Sta=236.7,258.11
XS Rating Curve= 0 ,0
Exp/Cntr(USF)=0,0
Exp/Cntr=0.3,0.1

Type RM Length L Ch R = 1 ,1161    ,350.8,355.3,351.1
XS GIS Cut Line= 4
2378603.41316459716816.8933286062378564.44756946717018.315481924
2378664.55917542717178.3741573292378782.65490222717262.300054545
#Sta/Elev= 30
       0 2379.93    16.6 2372.67    57.3 2357.37    74.7 2351.64   167.3 2322.71
   179.6 2319.88   212.2 2310.36   227.4 2303.16   241.6 2292.97   255.7  2286.1
   272.5 2275.54   279.3 2272.51   287.6 2271.21   302.7 2272.19     317 2268.88
   323.1 2268.43  332.57 2268.87   340.6 2270.54   360.9 2269.27   378.4 2270.04
   383.1 2271.06   403.3  2286.7   412.6 2297.26   419.5 2303.57   422.9 2305.92
     433 2309.67   447.3 2322.36   461.7 2328.13   487.5 2340.09   538.8 2366.85
#Mann= 3, -1 ,  0
       0     0.1       0     317   0.045       0  332.57     0.1       0
#XS Ineff= 2 , 0
                          375.49         2274.39
Permanent Ineff=
       F       F
Bank Sta=317,332.57
XS Rating Curve= 0 ,0
Exp/Cntr(USF)=0,0
Exp/Cntr=0.3,0.1

Type RM Length L Ch R = 1 ,806     ,199.7,195.1,191.9
XS GIS Cut Line= 4
2378235.31794091716899.3459061842378283.82236541717180.220364319
2378345.86290837717282.8692626732378538.75259648717383.262141283
#Sta/Elev= 30
       0 2313.87    91.2 2298.24   111.5 2296.05   119.6 2293.92   156.1 2289.32
   229.2 2276.65   273.8 2273.66   295.5 2270.96   303.5 2269.44   309.3 2267.16
   314.2 2264.02   323.5 2255.46   329.7 2251.04   347.2 2249.12     363 2248.41
   369.32249.058   379.6 2253.56     389 2253.38   399.6 2254.75   416.6 2254.12
   442.6  2255.9   479.7 2255.33   515.2 2256.86     527 2260.99   538.4 2267.02
   547.4 2270.51   574.4  2286.1     588 2289.15   598.2 2296.54   622.4 2309.92
#Mann= 3, -1 ,  0
       0     0.1       0   347.2   0.045       0   369.3     0.1       0
Bank Sta=347.2,369.3
XS Rating Curve= 0 ,0
Exp/Cntr(USF)=0,0
Exp/Cntr=0.3,0.1

Type RM Length L Ch R = 1 ,611     ,151.6,153.9,155.1
XS GIS Cut Line= 4
2378073.04470915716952.5179248972378089.28805131717306.825825709
2378311.61879709717467.2288295152378402.98759673717488.548216097
#Sta/Elev= 30
       0 2299.44   137.6 2287.11   188.9 2283.32     308 2272.28     345 2267.84
   354.7 2267.71   364.2 2265.19   368.1 2262.95   379.2 2254.47   392.8 2246.59
   422.4 2244.15   442.1 2243.63  460.222239.191   468.1 2238.49  476.422239.217
   488.6 2242.61   506.2 2241.55   525.9 2244.47   543.3 2244.71     557  2246.3
   577.5 2247.21   596.2 2247.13   613.4 2253.24     622 2258.28   629.4  2261.4
     654 2267.98   666.4 2268.68   674.6 2270.08   707.3  2283.7   722.7  2291.4
#Mann= 3, -1 ,  0
       0     0.1       0  460.22   0.045       0  476.42     0.1       0
Bank Sta=460.22,476.42
XS Rating Curve= 0 ,0
Exp/Cntr(USF)=0,0
Exp/Cntr=0.3,0.1

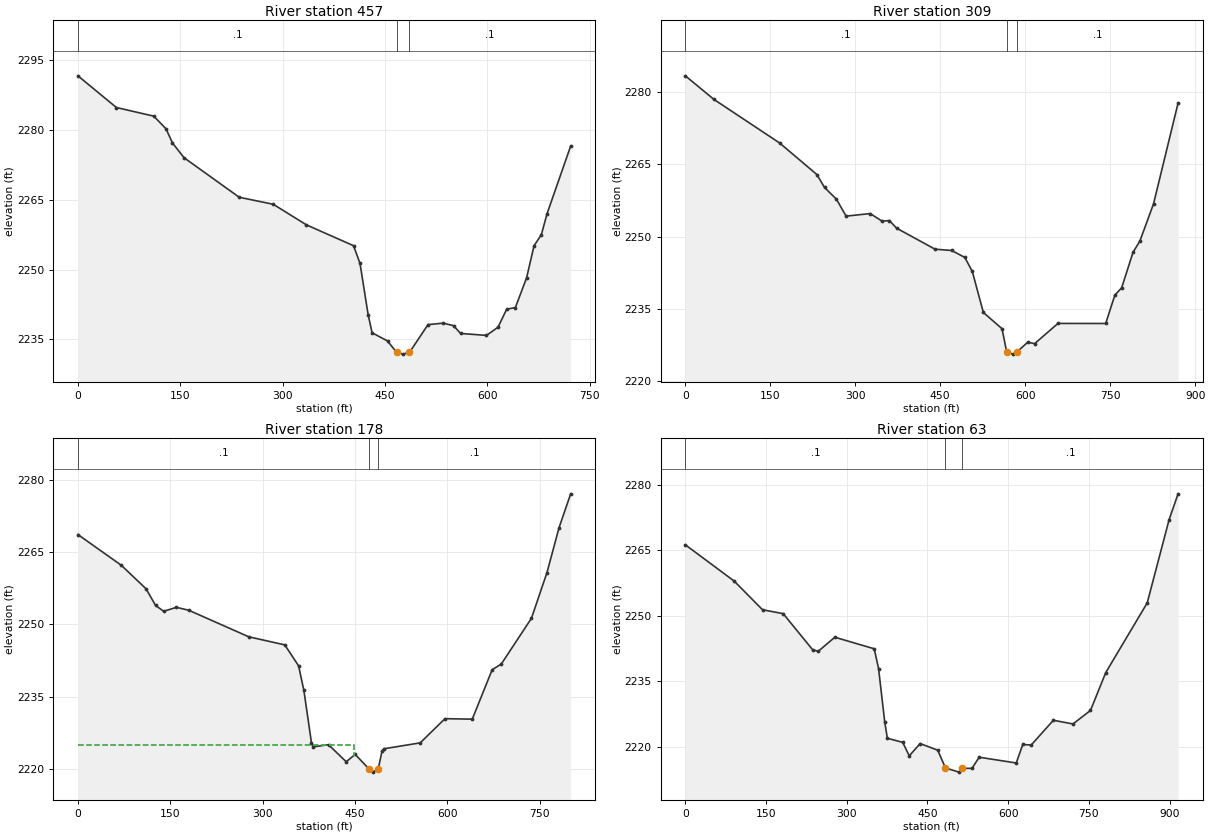
Type RM Length L Ch R = 1 ,457     ,153.1,148,142.6
XS GIS Cut Line= 4
2377842.27430226717087.7523761612378034.99519568717438.328017717
2378114.99574182717524.0692045032378308.91133417717590.631390747
#Sta/Elev= 30
       0  2291.7    56.4 2284.88   111.2 2283.02   129.1  2280.3   138.6 2277.25
   155.6 2274.07   236.4 2265.57   286.3 2264.06   334.8 2259.64     404 2255.14
   413.5 2251.33   425.5 2240.22   431.2 2236.41   453.8 2234.64   467.12232.198
   476.5 2231.81     486 2232.18   513.2 2238.16   535.5 2238.48   550.6 2237.93
   560.9 2236.26   598.9 2235.84   615.8  2237.6   628.5 2241.49   641.2 2241.82
   657.7 2248.23   668.6 2255.13   679.3 2257.51   687.7 2262.04   722.3 2276.59
#Mann= 3, -1 ,  0
       0     0.1       0   467.1   0.045       0     486     0.1       0
Bank Sta=467.1,486
XS Rating Curve= 0 ,0
Exp/Cntr(USF)=0,0
Exp/Cntr=0.3,0.1

Type RM Length L Ch R = 1 ,309     ,127.9,130.4,132.8
XS GIS Cut Line= 4
2377747.49207174717137.5649437162377905.41176927717584.362215137
2378079.57064284717626.8399891792378295.41192473717647.106276961
#Sta/Elev= 30
       0 2283.33    50.5 2278.44   166.4 2269.41   232.2 2262.87   245.7 2260.19
   266.7 2257.77   283.8 2254.25   326.3 2254.78   347.5  2253.2   360.2 2253.34
   372.9 2251.76   440.8  2247.4   470.2 2247.13   493.4 2245.69   506.6 2242.78
   526.1 2234.29   559.1 2230.91   567.3 2226.08   578.6 2225.65     5852226.057
   604.4 2228.11   616.7 2227.83   657.8 2232.01   742.1    2232   758.2 2237.86
   770.3 2239.41   790.4 2246.77   802.4 2249.08   826.5 2256.78   869.9  2277.7
#Mann= 3, -1 ,  0
       0     0.1       0   567.3   0.045       0     585     0.1       0
Bank Sta=567.3,585
XS Rating Curve= 0 ,0
Exp/Cntr(USF)=0,0
Exp/Cntr=0.3,0.1

Type RM Length L Ch R = 1 ,178     ,116.9,115.3,111.5
XS GIS Cut Line= 4
2377786.49659046717299.535968828 2377950.8511503717719.162192453
2377992.12153195717744.8569519352378290.81804962717708.959501611
#Sta/Elev= 30
       0  2268.6    70.5 2262.22   110.6 2257.35     126 2253.91   139.2 2252.68
     160  2253.5   180.1 2252.89   277.3 2247.39   335.9 2245.71   358.3 2241.36
   366.9 2236.25   379.2  2225.4   382.2 2224.55   406.9    2225   435.6 2221.46
   450.2 2222.99   472.12220.041   479.2 2219.31   487.72220.009   493.7 2223.62
   496.6 2224.15   555.7 2225.38     596  2230.4   640.3  2230.3   672.6 2240.55
   687.5 2241.75   736.4 2251.23   761.6 2260.71   781.3 2270.05   800.1 2277.05
#Mann= 3, -1 ,  0
       0     0.1       0   472.1   0.045       0   487.7     0.1       0
#XS Ineff= 2 , 0
          447.97 2224.85
Permanent Ineff=
       F       F
Bank Sta=472.1,487.7
XS Rating Curve= 0 ,0
Exp/Cntr(USF)=0,0
Exp/Cntr=0.3,0.1

Type RM Length L Ch R = 1 ,63      ,,,
XS GIS Cut Line= 4
2377781.34134849717324.0762207862377867.82997903717790.508120564
2377921.90154892717826.9954339392378292.75664276717764.391408335
#Sta/Elev= 30
       0 2266.21    90.6 2257.93   143.5 2251.35   181.8 2250.47   236.7 2242.19
     247 2241.86   277.8 2245.07     351 2242.43   359.1 2237.88   370.6 2225.61
   375.4 2221.97   403.9 2221.03   416.1 2217.95   436.4 2220.75     469 2219.23
  483.442215.174   508.6 2214.22   514.9  2215.1   532.7 2215.08     546 2217.63
   614.9 2216.31   627.1 2220.54   642.7 2220.42   683.9 2226.08   720.4 2225.24
   752.9 2228.33   781.3    2237   858.3 2252.92   898.9 2271.92   915.7 2277.87
#Mann= 3, -1 ,  0
       0     0.1       0  483.44   0.045       0   514.9     0.1       0
Bank Sta=483.44,514.9
XS Rating Curve= 0 ,0
Exp/Cntr(USF)=0,0
Exp/Cntr=0.3,0.1
LCMann Table=0

Chan Stop Cuts=-1
Use User Specified Reach Order=0
Composite Channel Slope=5